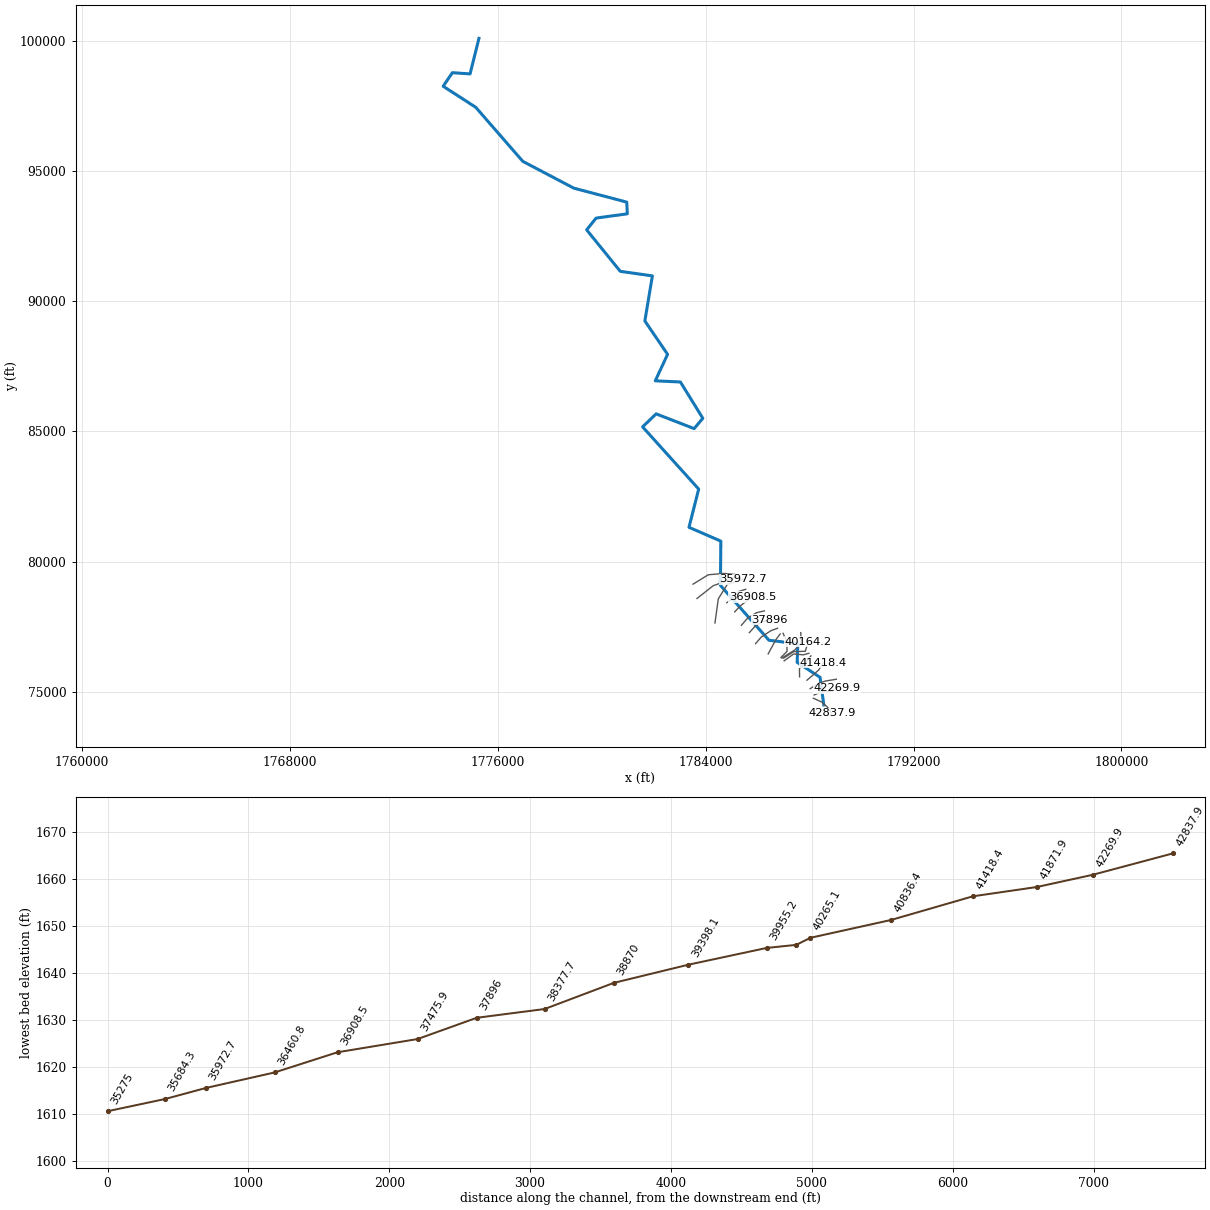
--- Dry Fork.prj (project) ---

Proj Title=Dry Fork
Current Plan=p01
Default Exp/Contr=0,0
English Units
Geom File=g01
Flow File=f01
Plan File=p01
BEGIN DESCRIPTION:
END DESCRIPTION:
DSS Export Rating Curves= 0
DSS Export Rating Curve Sorted= 0
DSS Export Volume Flow Curves= 0
DXF OffsetX= 0
DXF OffsetY= 0
DXF ScaleX= 0
DXF ScaleY= 0

--- Dry Fork.p01 (plan) ---

Plan Title=Floodplain
Program Version=4.00
Geom File=g01
Flow File=f01
K Sum by GR=0
Std Step Tol=0.01
Critical Tol=0.01
Num of Std Step Trials=20
Max Error Tol=0.3
Flow Tol Ratio=0.001
Split Flow NTrial=30
Split Flow Tol=0.02
Split Flow Ratio=0.02
Log Output Level=0
Friction Slope Method=1
Unsteady Friction Slope Method=2
Unsteady Bridges Friction Slope Method=1
Global Log Level=0
CheckData=False
Run HTab=0
Run UNet=0
Run PostProcess=0
UNET Theta=0
UNET Theta Warmup=0
UNET ZTol=0
UNET ZSATol=0
UNET MxIter=0
UNET MaxInSteps=0
UNET DtIC=0
UNET DtMin=0
UNET MaxCRTS=0
UNET WFStab=0
UNET SFStab=0
UNET WFX=0
UNET SFX=0
UNET DSS MLevel=0
UNET DZMax Abort=0
UNET Convert EG Bridges=0
UNET Use Existing IB Tables=0
UNET Froude Limit=0
UNET Froude Power=0
Write IC File=0
Echo Input=False
Echo Output=False
Write Detailed=0

--- Dry Fork.f01 (steady flow) ---

Flow Title=NFF Regression Equation
Program Version=4.00
Number of Profiles=1
Profile Names=P100yr
River Rch & RM=Dry Fork,Main      ,42837.9
4645.885
River Rch & RM=Dry Fork,Main      ,35972.7
4832.203
River Rch & RM=Dry Fork,Main      ,35684.3
6408.140
Boundary for River Rch & Prof#=Dry Fork,Main      ,1
Up Type=0
Dn Type=3
Dn Slope=0.007272

--- Dry Fork.g01 (geometry) ---

Geom Title=USGS 10m DEM
Program Version=4.00

River Reach=Dry Fork        ,Main
Reach XY= 30
     1788546.699       74487.839     1788402.841       75546.273
     1787522.174       76123.107       1787547.4       76838.965
     1786437.163       76971.999      1784568.49       79083.518
     1784585.214       80784.217     1783359.417       81315.645
     1783732.963       82786.171     1781573.802       85178.191
     1782095.726       85677.632     1783557.115       85110.742
     1783891.948       85507.592     1783029.168       86903.753
     1782062.404       86948.719      1782536.15       87967.676
     1781660.924        89251.61     1781951.107       90984.148
     1780715.437       91159.445     1779421.868       92753.321
     1779784.003       93206.191     1780986.035       93370.798
     1780964.355       93820.456     1778927.244       94357.637
     1776963.202       95389.441     1775152.526       97468.307
     1773899.907       98276.085     1774254.816       98798.009
     1774934.923       98750.635     1775277.415      100118.581

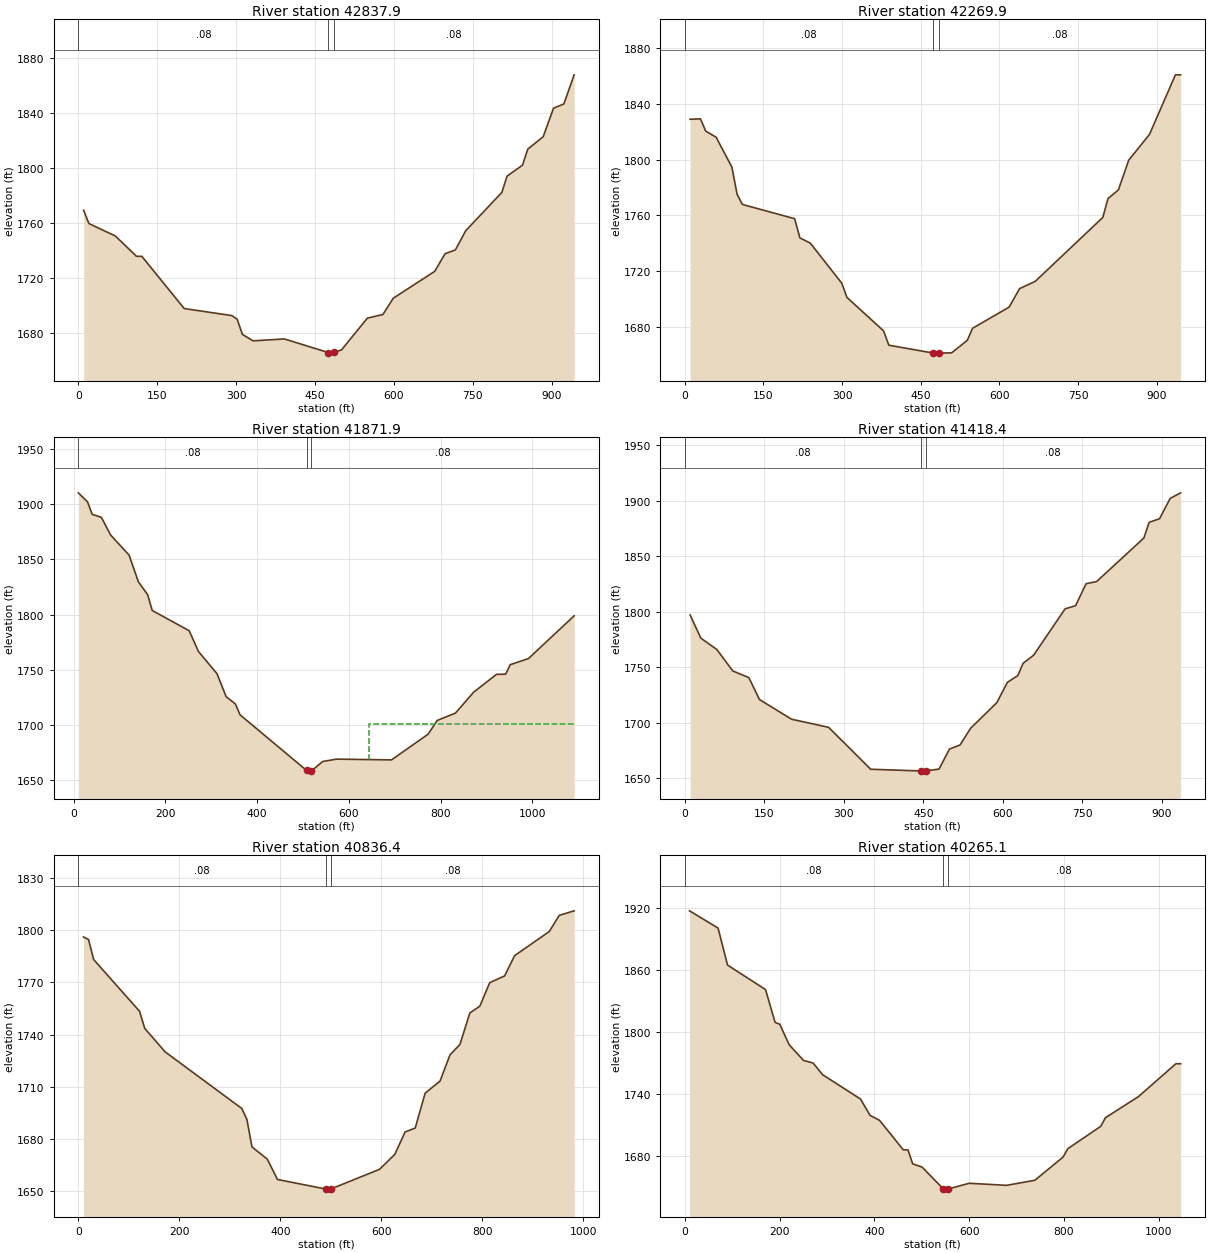
Type RM Length L Ch R = 1 ,42837.9 ,552.8,568,583.2
XS GIS Cut Line= 4
     1788145.346       74743.479     1788474.978       74592.984
     1788693.537       74393.867     1788856.985       74160.613
#Sta/Elev= 30
    10.1 1769.37    20.1 1759.74    70.5 1750.66   110.7 1735.89   120.8 1735.89
   201.3 1697.96   291.9 1692.83     302 1690.13     312 1679.17   332.2 1674.48
   391.9 1675.85   475.6 1665.93   480.6 1665.54   485.6 1666.13   500.3 1667.83
   549.6 1690.97   579.2 1693.62   598.9 1705.46   677.7 1724.99   697.3 1737.77
     717  1740.6   736.6 1754.51   805.3 1782.34   815.2 1794.19   844.6 1802.16
   854.5 1813.76   883.9 1822.83   903.6 1843.58   923.2 1846.63   942.8 1867.82
#Mann= 3 , 0 , 0
       0     .08       0   475.6    .045       0   485.6     .08       0
Bank Sta=475.6,485.6
XS Rating Curve= 0 ,0
Exp/Cntr=0.3,0.1

Type RM Length L Ch R = 1 ,42269.9 ,391.2,398,404.9
XS GIS Cut Line= 4
      1788176.32       74867.914     1788449.855       74989.226
     1788828.655       75004.135     1789064.292        75129.94
#Sta/Elev= 30
      10 1829.04    29.9 1829.32    39.9 1820.56    59.8 1816.07    89.8 1794.65
    99.7 1775.19   109.7 1767.85   209.5 1757.57   219.4 1743.83   239.4 1739.98
   299.2 1711.32   309.2 1701.02     379 1676.98     389 1666.69   473.8 1661.04
   478.8 1660.99   483.8 1661.02   508.7 1661.19   538.7 1670.18   548.6 1678.81
   618.5 1694.09   638.4 1707.35   668.3 1712.59     797 1758.49   806.9 1772.03
   826.7 1778.28   846.5 1799.64   886.1  1818.2   935.5 1860.97   945.4 1860.97
#Mann= 3 , 0 , 0
       0     .08       0   473.8    .045       0   483.8     .08       0
Bank Sta=473.8,483.8
XS Rating Curve= 0 ,0
Exp/Cntr=0.3,0.1

Type RM Length L Ch R = 1 ,41871.9 ,445.9,453.5,461.1
XS GIS Cut Line= 4
     1788019.818       75108.491     1788316.112        75299.56
     1788598.561       75402.017     1789030.542       75474.013
#Sta/Elev= 30
    10.1 1910.28    30.2 1902.09    40.3 1890.83    60.4 1888.06    80.6 1872.04
   120.9 1853.84     141 1829.73   161.2 1818.13   171.2 1803.79   251.8 1785.45
     272 1766.65   312.3 1746.63   332.4 1725.73   352.6 1719.12   362.6 1709.37
   507.8 1658.96   512.8 1658.38   517.8 1658.39   542.8  1667.1   572.9 1669.24
   692.8 1668.55   772.5 1691.77   792.4 1704.22   832.2  1710.9     872 1729.88
   921.8 1745.99   941.7 1746.12   951.6 1754.73   991.4 1760.27    1091 1798.96
#Mann= 3 , 0 , 0
    10.1     .08       0   507.8    .045       0   517.8     .08       0
#XS Ineff= 2 , 0
                          643.09         1701.34
Permanent Ineff=
       F       F
Bank Sta=507.8,517.8
XS Rating Curve= 0 ,0
Exp/Cntr=0.3,0.1

Type RM Length L Ch R = 1 ,41418.4 ,582.3,582,581.7
XS GIS Cut Line= 4
     1787899.156        75437.75     1788084.333       75592.891
     1788350.961       75830.142     1788532.928       76113.483
#Sta/Elev= 30
    10.1 1797.05    30.2 1776.26    60.4 1766.02    90.6 1746.65   120.8 1740.69
   140.9  1720.9   201.3 1703.19   271.3 1695.86   350.6  1658.1   444.8 1656.54
   449.8  1656.4   454.8 1656.59   479.5 1658.24   499.3 1676.32   519.2 1679.97
     539 1694.97   588.6 1718.15   608.4 1736.39   628.2 1742.54   638.1  1753.6
   657.9 1760.82   717.3 1802.64   737.1 1805.52   756.9 1825.32   776.8 1827.23
   865.9  1866.5   875.8 1880.56   895.6 1883.92   915.4 1902.15   935.2 1907.19
#Mann= 3 , 0 , 0
       0     .08       0   444.8    .045       0   454.8     .08       0
Bank Sta=444.8,454.8
XS Rating Curve= 0 ,0
Exp/Cntr=0.3,0.1

Type RM Length L Ch R = 1 ,40836.4 ,587.5,571.3,555
XS GIS Cut Line= 4
     1787614.316       75565.523     1787610.815       75889.186
     1787861.428       76124.101     1788054.294       76372.746
#Sta/Elev= 30
    10.1 1796.02    20.2 1794.59    30.3 1783.09   121.4 1753.33   131.5 1743.56
     172 1730.07   323.7 1697.62   333.8 1691.39   343.9 1675.56   374.2 1668.55
   394.4 1656.89   490.4 1651.38   495.4 1651.35   500.4 1651.46   596.5 1662.71
   626.8 1671.33     647 1684.09   667.2 1686.41   686.8  1706.4   716.3 1713.33
     736 1728.34   755.7 1734.35   775.4 1752.46     795 1756.27   814.7 1769.78
   844.2 1773.67   863.9 1785.27   932.7 1799.16   952.4  1808.4   981.9 1811.01
#Mann= 3 , 0 , 0
       0     .08       0   490.4    .045       0   500.4     .08       0
Bank Sta=490.4,500.4
XS Rating Curve= 0 ,0
Exp/Cntr=0.3,0.1

Type RM Length L Ch R = 1 ,40265.1 ,98.6,101,103.4
XS GIS Cut Line= 4
     1787021.501       76180.688     1787386.518       76445.776
     1787761.996       76412.305      1787971.84       76472.153
#Sta/Elev= 30
      10 1917.58    70.2 1900.85    90.2 1864.93   170.4 1841.18   190.5  1809.4
   200.5 1807.49   220.5 1787.49   250.6  1772.4   270.7 1769.95   290.7 1758.63
   370.9 1734.94     391  1719.1     411  1714.3     461 1685.72     471 1685.59
   480.9 1672.08   500.7 1668.96   545.3 1647.89   550.3 1647.56   555.3 1647.64
   599.9 1653.23   679.3 1651.24   738.8 1656.19   798.3 1678.67   808.2 1686.78
   877.7 1708.45   887.6 1716.84     957 1737.21  1036.4 1769.25  1046.3  1769.2
#Mann= 3 , 0 , 0
       0     .08       0   545.3    .045       0   555.3     .08       0
Bank Sta=545.3,555.3
XS Rating Curve= 0 ,0
Exp/Cntr=0.3,0.1

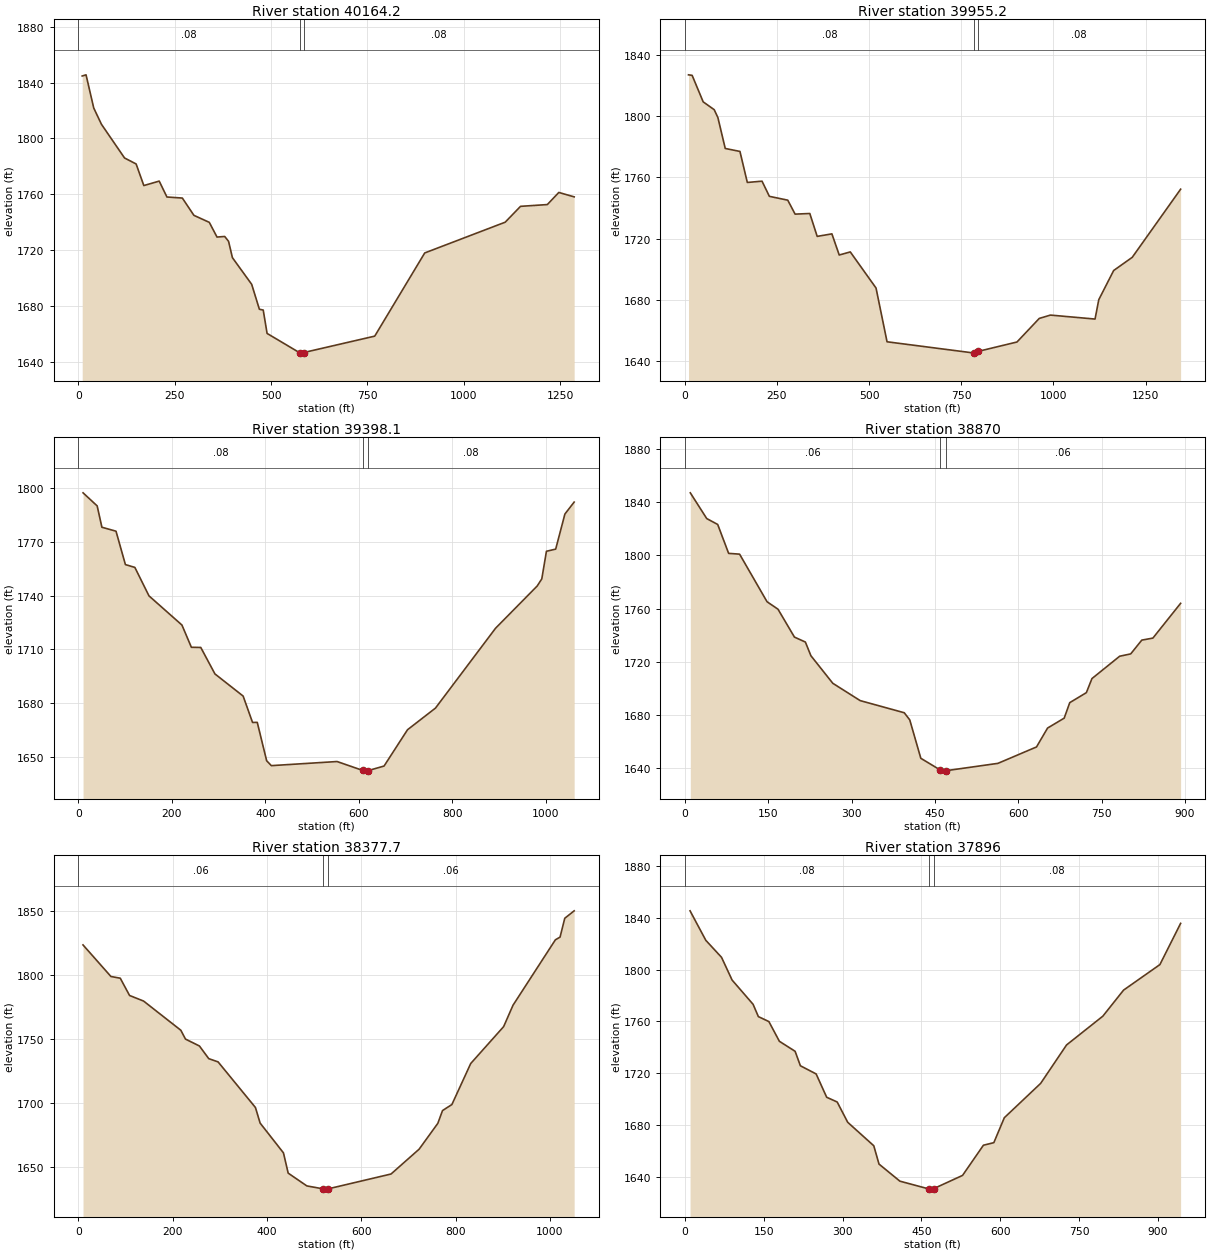
Type RM Length L Ch R = 1 ,40164.2 ,182,209,234.2
XS GIS Cut Line= 4
     1787000.616       76284.675     1787386.518       76534.388
     1787835.113       76548.233     1787942.909       76910.137
#Sta/Elev= 30
      10 1844.76      20  1845.6      40 1821.78      60 1810.12   119.9 1785.97
   149.9 1781.69   169.9  1766.2   209.8 1769.39   229.8    1758   269.8 1757.24
   299.8 1744.84   339.7 1739.82   359.7 1729.28   379.7  1729.7   389.7  1726.2
   399.7 1714.49   449.7 1695.37   469.6 1677.52   479.6 1676.93   489.6 1660.18
   574.3 1646.28   579.3 1646.05   584.3 1646.44   768.8 1658.23   898.5 1717.88
  1107.2 1739.93    1147  1751.3  1216.5 1752.57  1246.3 1761.25  1286.1  1758.1
#Mann= 3 , 0 , 0
       0     .08       0   574.3    .045       0   584.3     .08       0
Bank Sta=574.3,584.3
XS Rating Curve= 0 ,0
Exp/Cntr=0.3,0.1

Type RM Length L Ch R = 1 ,39955.2 ,551.9,557.1,564
XS GIS Cut Line= 4
     1786935.153       76287.937     1787433.592       76600.846
     1787674.505       76872.219     1787660.659       77265.432
#Sta/Elev= 30
      10 1826.92    19.9 1826.57    49.9 1809.28    79.8 1804.18    89.8 1799.02
   109.7 1778.89   149.6 1776.95   169.6 1756.72   209.5 1757.55   229.4 1747.67
   279.3 1745.16   299.2 1736.06   339.1 1736.47   359.1 1721.54     399 1723.19
   418.9  1709.4   448.9 1711.41   518.7 1687.88   548.6  1652.8   785.1 1645.45
   790.1  1645.4   795.1  1646.5     901 1652.65   961.5 1668.04   991.8 1670.21
  1112.8 1667.62  1122.9 1680.25  1163.3 1699.28  1213.7 1707.89  1344.9 1752.32
#Mann= 3 , 0 , 0
       0     .08       0   785.1    .045       0   795.1     .08       0
Bank Sta=785.1,795.1
XS Rating Curve= 0 ,0
Exp/Cntr=0.3,0.1

Type RM Length L Ch R = 1 ,39398.1 ,539,528,517
XS GIS Cut Line= 4
     1786899.707       76310.124     1787134.529       76545.464
     1787120.683       76946.985     1786977.337       77240.097
#Sta/Elev= 30
    10.1 1797.55    40.3 1790.23    50.4  1778.3    80.6 1776.07   100.7 1757.39
   120.9 1755.82   151.1 1739.89   221.6 1723.57   241.8 1711.12   261.9 1711.02
   292.2 1696.21   352.5 1683.82   372.6 1669.06   382.7  1669.1   402.8 1647.62
   412.8 1644.89   553.4 1647.19   608.7 1642.18   613.7 1641.82   618.7 1642.03
   653.9 1644.66   704.1 1664.98   763.9  1677.1   892.4 1721.78   981.4  1745.4
   991.3 1749.41  1001.2 1764.84    1021 1766.05  1040.7 1785.69  1060.5 1792.37
#Mann= 3 , 0 , 0
       0     .08       0   608.7    .045       0   618.7     .08       0
Bank Sta=608.7,618.7
XS Rating Curve= 0 ,0
Exp/Cntr=0.3,0.1

Type RM Length L Ch R = 1 ,38870   ,502.1,492.4,482.7
XS GIS Cut Line= 4
     1786407.936       76449.443     1786561.323       76736.533
     1786715.935       77013.655     1786865.925       77212.819
#Sta/Elev= 30
     9.9 1847.09    39.5 1827.73    59.2 1823.32    78.9 1801.59    98.6 1801.01
     148 1765.25   167.7 1759.64   197.3 1738.68     217 1734.95   226.9 1724.69
   266.3 1703.97   315.6 1690.95   394.9 1681.83   404.8 1676.48   424.7 1647.62
   459.3  1638.9   464.3 1637.96   469.3 1638.24   563.5  1643.8   632.9 1656.14
   652.8 1670.33   682.7 1677.78   692.7 1689.42   722.6 1696.93   732.6 1707.48
   782.5  1724.3   802.4 1726.06   822.3  1736.4   842.3 1737.93   892.2 1764.06
#Mann= 3 , 0 , 0
       0     .06       0   459.3    .045       0   469.3     .06       0
Bank Sta=459.3,469.3
XS Rating Curve= 0 ,0
Exp/Cntr=0.3,0.1

Type RM Length L Ch R = 1 ,38377.7 ,481.4,481.7,482
XS GIS Cut Line= 4
      1785921.66       76841.759     1786140.419       77096.517
     1786513.686       77340.984     1786766.237       77434.348
#Sta/Elev= 30
     9.9 1823.79    69.1 1799.03    88.9  1797.7   108.6 1784.16   138.3 1779.79
   217.3 1756.91   227.2 1749.97   256.8 1744.54   276.5 1734.65   296.3  1732.1
   375.5 1696.35   385.4 1684.16   434.9 1660.79   444.9 1644.92   484.5 1634.89
   519.2 1632.58   524.2 1632.38   529.2 1632.56     663 1644.23   722.5 1663.68
   762.2 1683.96   772.1 1693.95     792 1698.69   831.9 1730.82   901.7 1759.75
   921.6 1776.53  1011.4 1827.79  1021.3 1829.89  1031.3 1844.66  1051.2  1850.5
#Mann= 3 , 0 , 0
       0     .06       0   519.2    .045       0   529.2     .06       0
Bank Sta=519.2,529.2
XS Rating Curve= 0 ,0
Exp/Cntr=0.3,0.1

Type RM Length L Ch R = 1 ,37896   ,420.9,420.1,419.3
XS GIS Cut Line= 4
     1785680.747       77265.432      1785888.43       77495.268
     1786143.381       77667.646     1786453.328       77766.641
#Sta/Elev= 30
      10 1845.46      40 1822.67    69.9 1809.52    89.9 1792.02   129.9 1773.25
   139.9 1763.76   159.9 1759.93   179.9 1744.68   209.8 1736.97   219.8  1725.8
   249.8 1719.47   269.8 1701.48   289.8  1697.8   309.8 1682.14   359.4 1664.01
   369.3 1649.86     409 1636.67   463.6  1630.7   468.6 1630.51   473.6 1630.93
   528.2 1641.11   567.9 1664.42   587.7 1666.39   607.6 1685.65   676.7 1712.17
     726 1741.87     795  1764.1   834.4 1784.21   903.5 1803.94   942.9 1835.77
#Mann= 3 , 0 , 0
       0     .08       0   463.6    .045       0   473.6     .08       0
Bank Sta=463.6,473.6
XS Rating Curve= 0 ,0
Exp/Cntr=0.3,0.1

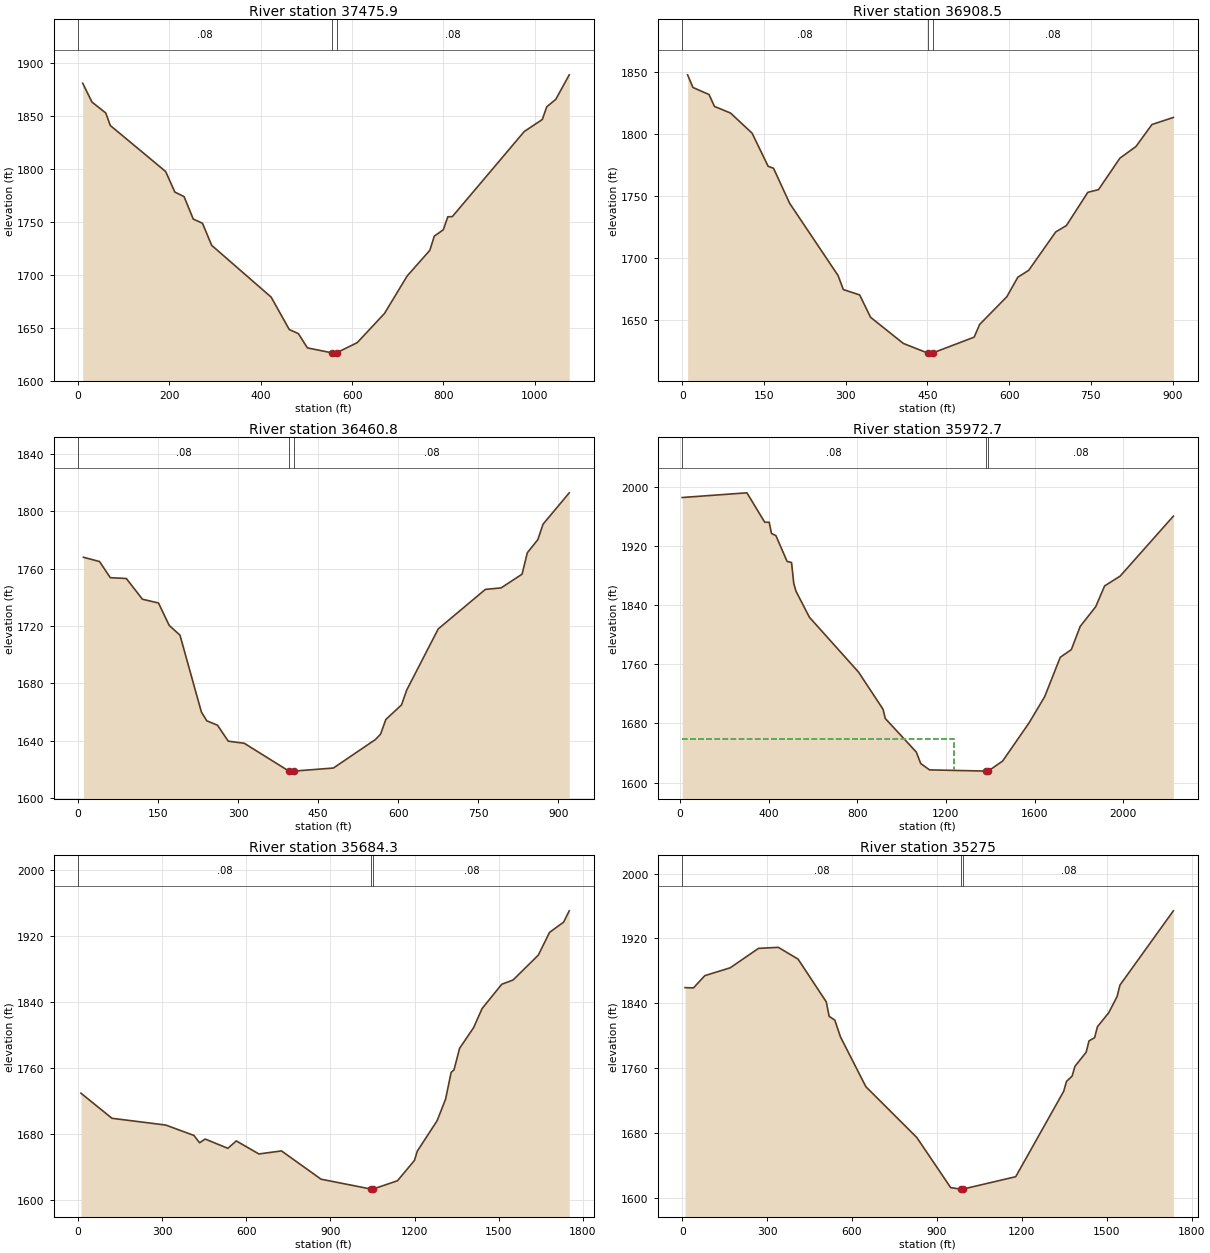
Type RM Length L Ch R = 1 ,37475.9 ,565.2,567.4,569.6
XS GIS Cut Line= 4
     1785376.145       77547.881     1785614.289       77822.023
     1785952.515       78030.071     1786259.491       78101.703
#Sta/Elev= 30
    10.1 1880.66    30.3 1862.95    60.5 1852.61    70.6 1840.76   191.7 1797.37
   211.8 1777.99     232 1773.71   252.2 1752.47   272.3 1748.57   292.5  1727.7
   422.7 1678.85   462.4 1648.24   482.3 1644.39   502.1 1630.92   556.7 1626.18
   561.7 1625.98   566.7 1626.45   611.3 1635.91   670.9 1663.45   720.5 1698.78
   770.1    1723   779.9 1736.38   799.6 1742.39   809.5 1754.67   819.3 1754.77
   976.9 1835.12  1016.3 1846.41  1026.2 1858.47  1045.9 1865.47  1075.4  1888.6
#Mann= 3 , 0 , 0
       0     .08       0   556.7    .045       0   566.7     .08       0
Bank Sta=556.7,566.7
XS Rating Curve= 0 ,0
Exp/Cntr=0.3,0.1

Type RM Length L Ch R = 1 ,36908.5 ,442.4,447.7,453
XS GIS Cut Line= 4
     1785118.618       78062.935     1785326.301       78287.233
     1785610.778       78508.369     1785809.015       78635.499
#Sta/Elev= 30
     9.9 1848.08    19.7 1837.87    49.3 1832.13    59.2 1822.57    88.7 1817.19
   128.2 1800.99   157.8 1774.14   167.6 1772.59   197.2 1744.26     286 1685.95
   295.8 1674.52   325.7 1670.21   345.7 1652.17   405.8 1631.02   450.8  1623.2
   455.8 1623.17   460.8 1623.47   535.9 1636.09   545.9 1646.31   595.9 1668.78
     616 1684.52     636 1690.09   685.6 1721.12   705.2 1726.27   744.5 1753.12
   764.1 1755.29   803.4 1780.74   832.8 1790.12   862.2 1807.93   901.5 1813.63
#Mann= 3 , 0 , 0
       0     .08       0   450.8    .045       0   460.8     .08       0
Bank Sta=450.8,460.8
XS Rating Curve= 0 ,0
Exp/Cntr=0.3,0.1

Type RM Length L Ch R = 1 ,36460.8 ,486.4,488.1,489.8
XS GIS Cut Line= 4
     1784813.467       78413.988     1785063.236       78600.142
     1785240.459       78835.516     1785539.523       78932.435
#Sta/Elev= 30
      10  1767.9    40.2 1764.93    60.3 1753.68    90.4 1753.11   120.6 1738.66
   150.7 1736.03   170.8 1720.39   190.9 1713.66   231.1 1660.02   241.2 1653.93
   261.3 1650.86   281.4 1639.74   311.5 1638.25   394.9 1618.93   399.9 1618.86
   404.9 1618.89   478.5 1621.02     557 1640.81   566.9 1644.62   576.7 1654.84
   606.1    1665     616 1675.46   674.9 1717.95   763.3 1745.52   792.8 1746.55
   832.1 1756.13   841.9 1771.03   861.6 1780.19   871.4 1790.96   920.5 1812.81
#Mann= 3 , 0 , 0
       0     .08       0   394.9    .045       0   404.9     .08       0
Bank Sta=394.9,404.9
XS Rating Curve= 0 ,0
Exp/Cntr=0.3,0.1

Type RM Length L Ch R = 1 ,35972.7 ,302,288.4,274.8
XS GIS Cut Line= 4
     1784358.668       77636.596     1784487.262       78564.144
     1784836.169       79123.504     1785437.066       79314.572
#Sta/Elev= 30
    10.1 1985.53   302.1 1991.86   382.6 1952.07   402.8 1952.09   412.8 1936.99
     433 1933.98   483.3 1899.16   503.5  1897.6   513.5 1869.23   523.6 1858.76
     584 1823.66   805.5 1749.56   916.3 1699.22   926.4 1686.75  1066.3 1641.35
  1086.3 1625.82  1126.2 1617.23  1380.9  1615.6  1385.9 1615.55  1390.9 1615.68
  1455.8 1629.17  1575.7 1681.03  1645.7 1716.31  1715.8 1769.46  1765.8 1779.83
  1805.9 1811.25  1875.9 1837.89    1916 1866.01    1986  1879.2  2226.2 1960.33
#Mann= 3 , 0 , 0
    10.1     .08       0  1380.9    .045       0  1390.9     .08       0
#XS Ineff= 2 , 0
         1238.15 1658.49
Permanent Ineff=
       F       F
Bank Sta=1380.9,1390.9
XS Rating Curve= 0 ,0
Exp/Cntr=0.3,0.1

Type RM Length L Ch R = 1 ,35684.3 ,414.2,409.2,403.7
XS GIS Cut Line= 4
     1783667.362       78579.286     1784293.424       79070.891
     1784769.711       79237.037     1785182.308       79419.798
#Sta/Elev= 30
    10.1 1729.62   120.9 1699.14   312.4 1690.96   413.1 1678.35   433.3 1669.48
   453.4 1673.98     534 1662.73   564.3 1671.69   644.9 1655.88   725.5 1659.57
   866.6 1625.25  1043.2 1613.39  1048.2 1613.21  1053.2 1613.48    1139 1623.35
  1199.6 1648.05  1209.6 1659.21  1280.3 1696.13  1310.5 1722.24  1330.5 1754.91
  1340.6 1757.82  1360.6 1784.06  1410.8 1809.25  1440.8 1832.29    1511 1861.79
  1551.1 1866.87  1641.4 1897.16  1681.5 1924.76  1731.6 1937.14  1751.7 1950.86
#Mann= 3 , 0 , 0
       0     .08       0  1043.2    .045       0  1053.2     .08       0
Bank Sta=1043.2,1053.2
XS Rating Curve= 0 ,0
Exp/Cntr=0.3,0.1

Type RM Length L Ch R = 1 ,35275   ,35291.8,35275,35258.8
XS GIS Cut Line= 4
     1783515.484       79129.189     1784102.047       79490.554
     1784699.084       79542.925     1785144.243       79501.028
#Sta/Elev= 30
      10 1859.31    39.9 1859.02    79.9  1874.1   169.7 1883.82   269.6 1907.79
   339.5 1909.08   409.4 1894.53   509.2 1841.67   519.2 1823.89   539.2 1819.31
   559.1 1798.58     649 1737.01   828.8  1674.4   948.7 1612.44   983.6 1610.61
   988.6  1610.6   993.6 1610.79  1178.4 1625.93  1347.9 1731.35  1357.8 1743.58
  1377.7 1750.15  1387.6 1762.18  1427.4 1779.64  1437.3 1793.56  1457.2  1797.6
  1467.1 1811.06  1506.9 1828.26  1536.7 1848.37  1546.6 1862.41  1735.4 1954.14
#Mann= 3 , 0 , 0
       0     .08       0   983.6    .045       0   993.6     .08       0
Bank Sta=983.6,993.6
XS Rating Curve= 0 ,0
Exp/Cntr=0.3,0.1
Stream Node=Dry Fork        ,Main            , 0 , 0 ,Upstream end
Stream Node=Dry Fork        ,Main            , 0 , 1 ,Downstream end

Chan Stop Cuts=-1
Use User Specified Reach Order=0